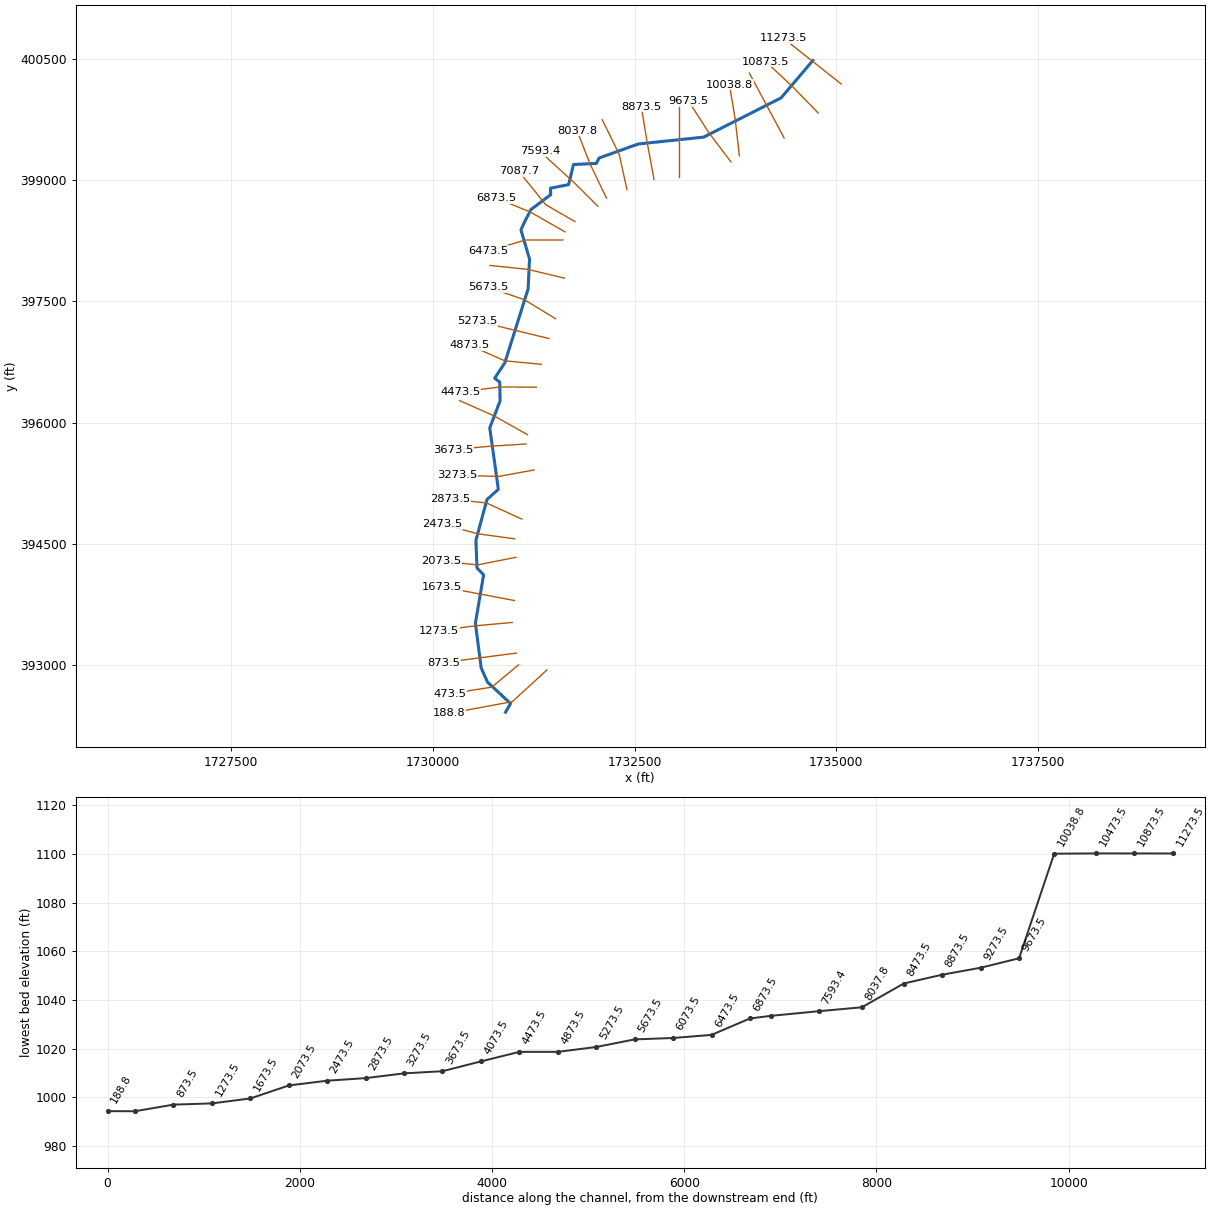
--- NP9.prj (project) ---

Proj Title=NP9
Current Plan=p01
Default Exp/Contr=0,0
English Units
Geom File=g01
Flow File=f01
Plan File=p01
BEGIN DESCRIPTION:
END DESCRIPTION:
DSS Export Rating Curves= 0
DSS Export Rating Curve Sorted= 0
DSS Export Volume Flow Curves= 0
DXF OffsetX= 0
DXF OffsetY= 0
DXF ScaleX= 0
DXF ScaleY= 0

--- NP9.p01 (plan) ---

Plan Title=Floodplain
Program Version=4.00
Geom File=g01
Flow File=f01
K Sum by GR=0
Std Step Tol=0.01
Critical Tol=0.01
Num of Std Step Trials=20
Max Error Tol=0.3
Flow Tol Ratio=0.001
Split Flow NTrial=30
Split Flow Tol=0.02
Split Flow Ratio=0.02
Log Output Level=0
Friction Slope Method=1
Unsteady Friction Slope Method=2
Unsteady Bridges Friction Slope Method=1
Global Log Level=0
CheckData=False
Run HTab=0
Run UNet=0
Run PostProcess=0
UNET Theta=0
UNET Theta Warmup=0
UNET ZTol=0
UNET ZSATol=0
UNET MxIter=0
UNET MaxInSteps=0
UNET DtIC=0
UNET DtMin=0
UNET MaxCRTS=0
UNET WFStab=0
UNET SFStab=0
UNET WFX=0
UNET SFX=0
UNET DSS MLevel=0
UNET DZMax Abort=0
UNET Convert EG Bridges=0
UNET Use Existing IB Tables=0
UNET Froude Limit=0
UNET Froude Power=0
Write IC File=0
Echo Input=False
Echo Output=False
Write Detailed=0

--- NP9.f01 (steady flow) ---

Flow Title=NFF Regression Equation
Program Version=4.00
Number of Profiles=1
Profile Names=P100yr
River Rch & RM=NP9,Main      ,11273.5
     722
River Rch & RM=NP9,Main      ,10038.8
776.3647
River Rch & RM=NP9,Main      ,7593.4
851.4480
River Rch & RM=NP9,Main      ,7593.4
1168.782
River Rch & RM=NP9,Main      ,6473.5
1253.115
River Rch & RM=NP9,Main      ,4073.5
1389.331
River Rch & RM=NP9,Main      ,188.8
1509.206
Boundary for River Rch & Prof#=NP9,Main      ,1
Up Type=0
Dn Type=3
Dn Slope=0.006067

--- NP9.g01 (geometry) ---

Geom Title=USGS 3m DEM
Program Version=4.00

River Reach=NP9             ,Main
Reach XY= 30
     1734708.836      400481.085      1734316.04      400018.845
     1733356.839      399532.734     1732547.377      399448.099
     1732061.266      399274.488     1732026.544      399207.213
     1731744.426      399194.192     1731683.662      398944.626
     1731460.138      398901.223     1731462.308      398820.928
     1731217.082      398636.466     1731136.787      398480.216
     1731093.384       398384.73     1731199.721      398024.487
      1731182.36      397655.564     1730893.731      396739.765
     1730767.863      396548.793     1730830.797       396501.05
     1730835.138      396268.845     1730707.099      395934.644
     1730813.436      395175.095     1730672.377      395047.057
     1730535.658      394543.585     1730548.679      394200.703
     1730631.145      394116.067     1730529.148      393517.109
     1730600.762      392965.894     1730678.888      392787.942
     1730965.346      392523.185     1730902.742       392416.88

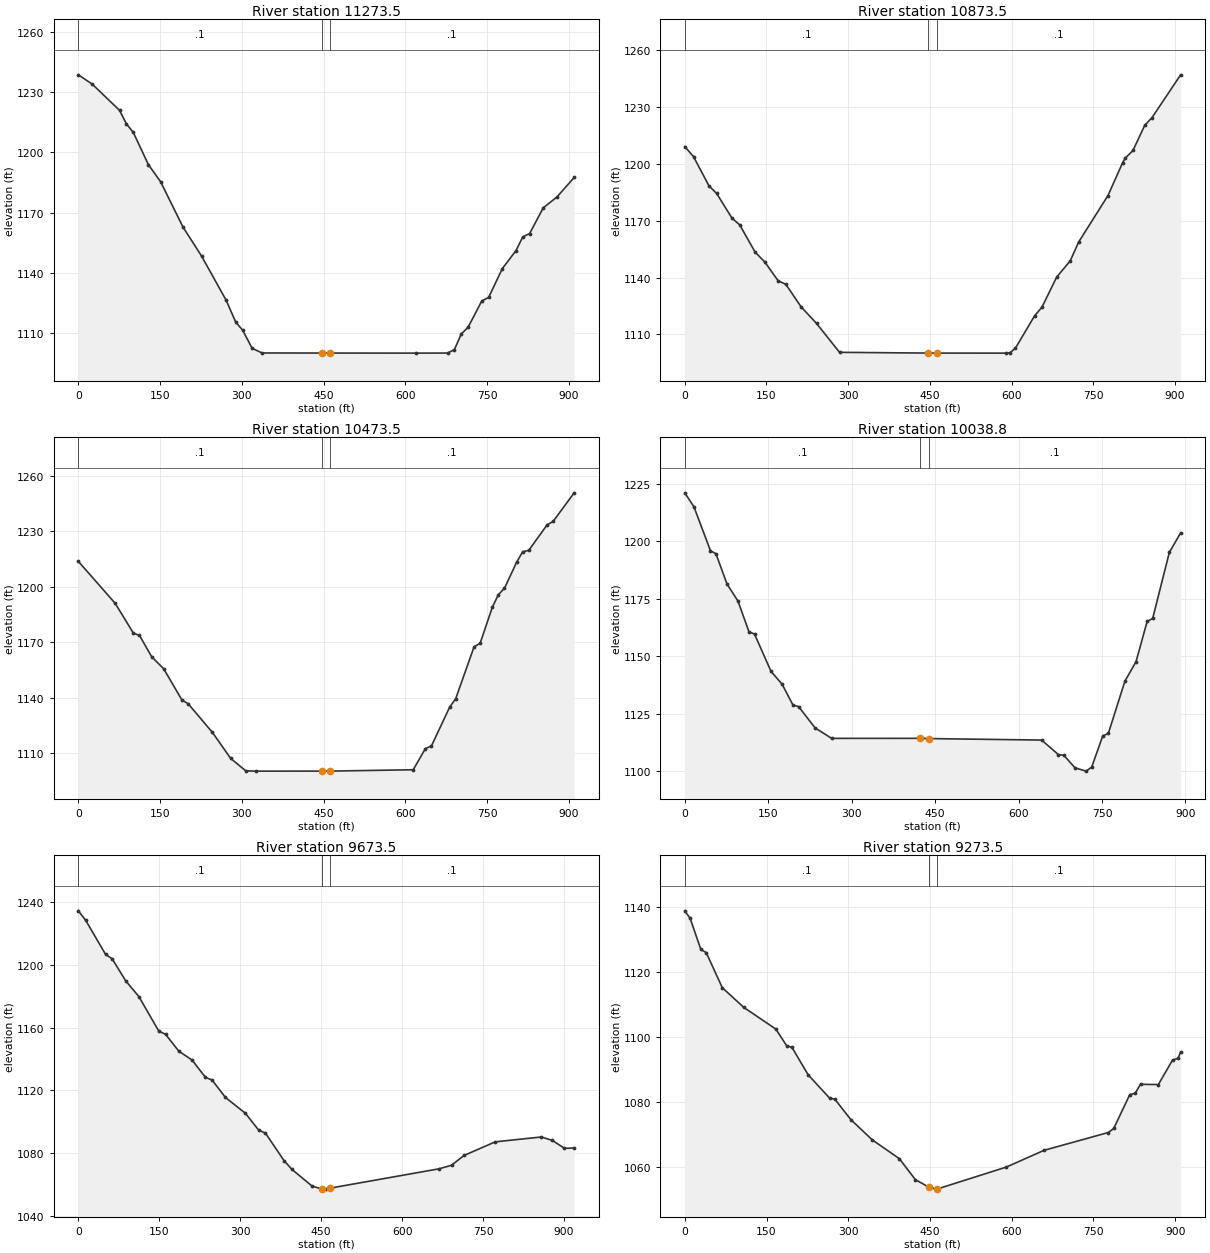
Type RM Length L Ch R = 1 ,11273.5 ,402.944,400,398.115
XS GIS Cut Line= 3
     1735059.609      400191.114     1734702.635      400473.239
     1734345.661      400755.364
#Sta/Elev= 30
       0 1238.59    25.6 1233.94    75.7 1220.91    88.3 1214.16   100.8 1209.99
   128.5 1193.95     151 1185.41     192 1162.91   226.2 1148.42   271.3 1126.46
   288.9 1115.57   301.5 1111.59     319 1102.56   337.2 1100.24   447.5  1100.2
   462.5  1100.2   620.1 1100.16   677.7  1100.2   690.3 1101.95   702.8 1109.67
   715.4 1113.07   740.5 1126.13     753 1127.83   778.1  1142.2   803.2 1151.14
   815.7 1157.97   828.2 1159.63   853.3 1172.43   878.4 1177.82     910 1187.53
#Mann= 3 , 0 , 0
       0      .1       0   447.5    .045       0   462.5      .1       0
Bank Sta=447.5,462.5
XS Rating Curve= 0 ,0
Exp/Cntr=0.3,0.1

Type RM Length L Ch R = 1 ,10873.5 ,406.325,400,392.616
XS GIS Cut Line= 3
     1734775.286      399830.946     1734458.127      400157.039
     1734125.468      400468.358
#Sta/Elev= 30
       0 1209.02    16.1 1203.71    44.4 1188.35    58.5 1184.33    86.7  1171.3
   100.8  1167.8     129 1153.48   146.9 1148.21   171.4 1138.33   185.5 1136.46
   213.7 1124.53   241.9 1115.84   284.2  1100.6   447.4  1100.2   462.4  1100.2
   590.5 1100.18   597.4 1100.42     607 1102.73   642.4 1119.87   655.9  1124.4
   682.8 1140.21   707.8 1148.85   723.2  1158.7   777.1 1183.25   804.1  1200.6
   808.6 1202.89     823 1206.99   844.5  1220.2     858 1224.33   910.5 1246.86
#Mann= 3 , 0 , 0
       0      .1       0   447.4    .045       0   462.4      .1       0
Bank Sta=447.4,462.4
XS Rating Curve= 0 ,0
Exp/Cntr=0.3,0.1

Type RM Length L Ch R = 1 ,10473.5 ,443.27,434.705,426.411
XS GIS Cut Line= 3
     1734353.224      399522.495     1734138.202      399923.483
      1733923.18       400324.47
#Sta/Elev= 30
       0 1213.79    67.6 1191.08     101 1174.95   112.2 1173.69   134.5 1162.21
   156.8 1155.55   190.3 1138.64   201.5 1136.72   246.2 1121.11   279.7 1107.04
   307.4 1100.33   325.7 1100.19   447.5  1100.2   462.5  1100.2   614.6 1100.94
     637  1112.4   648.1 1113.87   681.6 1134.88   692.6 1139.43   726.3 1167.51
   737.4 1169.42   759.8 1188.91   770.9 1195.75   782.1 1199.22   804.4 1213.33
   815.6 1219.01   826.8 1219.78   860.3 1233.56   871.4 1235.42     910 1250.91
#Mann= 3 , 0 , 0
       0      .1       0   447.5    .045       0   462.5      .1       0
Bank Sta=447.5,462.5
XS Rating Curve= 0 ,0
Exp/Cntr=0.3,0.1

Type RM Length L Ch R = 1 ,10038.8 ,353.131,365.295,375.357
XS GIS Cut Line= 3
     1733799.091      399300.072     1733748.212      399745.706
     1733676.279      400182.568
#Sta/Elev= 30
       0 1221.04    16.4 1214.99    46.1 1195.89      56 1194.54    75.8 1181.45
    95.6 1173.98   115.4 1160.62   125.3 1159.66     155 1143.43   174.8  1137.9
   194.6 1128.73   204.5 1128.15   234.2 1118.86     264 1114.31   423.6 1114.32
   438.6 1114.22   641.6 1113.57   671.5 1107.26   681.5 1106.94   701.5 1101.49
   721.4 1100.07   731.4 1101.81   751.3 1115.38   761.3 1116.43   791.2  1139.2
   811.2 1147.67   831.1 1165.13   841.1 1166.44     871 1195.14   891.3 1203.63
#Mann= 3 , 0 , 0
       0      .1       0   423.6    .045       0   438.6      .1       0
Bank Sta=423.6,438.6
XS Rating Curve= 0 ,0
Exp/Cntr=0.3,0.1

Type RM Length L Ch R = 1 ,9673.5  ,415.018,400,386.814
XS GIS Cut Line= 3
     1733694.378      399226.902      1733417.05      399592.945
     1733169.207      399980.022
#Sta/Elev= 30
       0 1234.34    13.4 1228.43    50.5  1206.6    62.8 1203.78    87.5 1189.87
   112.2 1179.73   149.2 1157.71   161.6 1155.74   186.3 1144.95   210.9  1139.3
   235.6  1128.3     248 1126.55   272.7  1115.5   309.7  1105.4   334.4 1094.62
   346.7 1092.84   381.2  1075.3   396.1 1069.63   433.2 1059.05   451.7 1057.19
   459.2 1057.13   466.7 1057.76   668.2 1070.05   691.6 1072.33     715  1078.6
   772.7 1087.24   858.1 1090.33   878.6 1088.14   900.9 1083.13   918.9  1083.3
#Mann= 3 , 0 , 0
       0      .1       0   451.7    .045       0   466.7      .1       0
Bank Sta=451.7,466.7
XS Rating Curve= 0 ,0
Exp/Cntr=0.3,0.1

Type RM Length L Ch R = 1 ,9273.5  ,395.795,400,403.473
XS GIS Cut Line= 3
     1733045.265      399040.842     1733045.265      399495.842
     1733045.265      399950.842
#Sta/Elev= 30
       0 1138.97     9.8 1136.65    29.5 1127.06    39.3 1126.11    68.8 1115.29
   108.2 1109.23   167.2 1102.53   186.9 1097.42   196.8 1096.88   226.3 1088.48
   265.6 1081.31   275.5 1080.92     305  1074.6   344.4 1068.37   393.6 1062.65
   423.1 1056.19   447.5 1053.87   462.4 1053.24   462.5 1053.24   590.4 1060.05
   659.2 1065.19   777.3 1070.68   787.2 1071.92   816.7 1082.36   826.5 1082.76
   836.4 1085.53   869.1 1085.45   895.4 1093.07   905.2 1093.51     910 1095.47
#Mann= 3 , 0 , 0
       0      .1       0   447.5    .045       0   462.5      .1       0
Bank Sta=447.5,462.5
XS Rating Curve= 0 ,0
Exp/Cntr=0.3,0.1

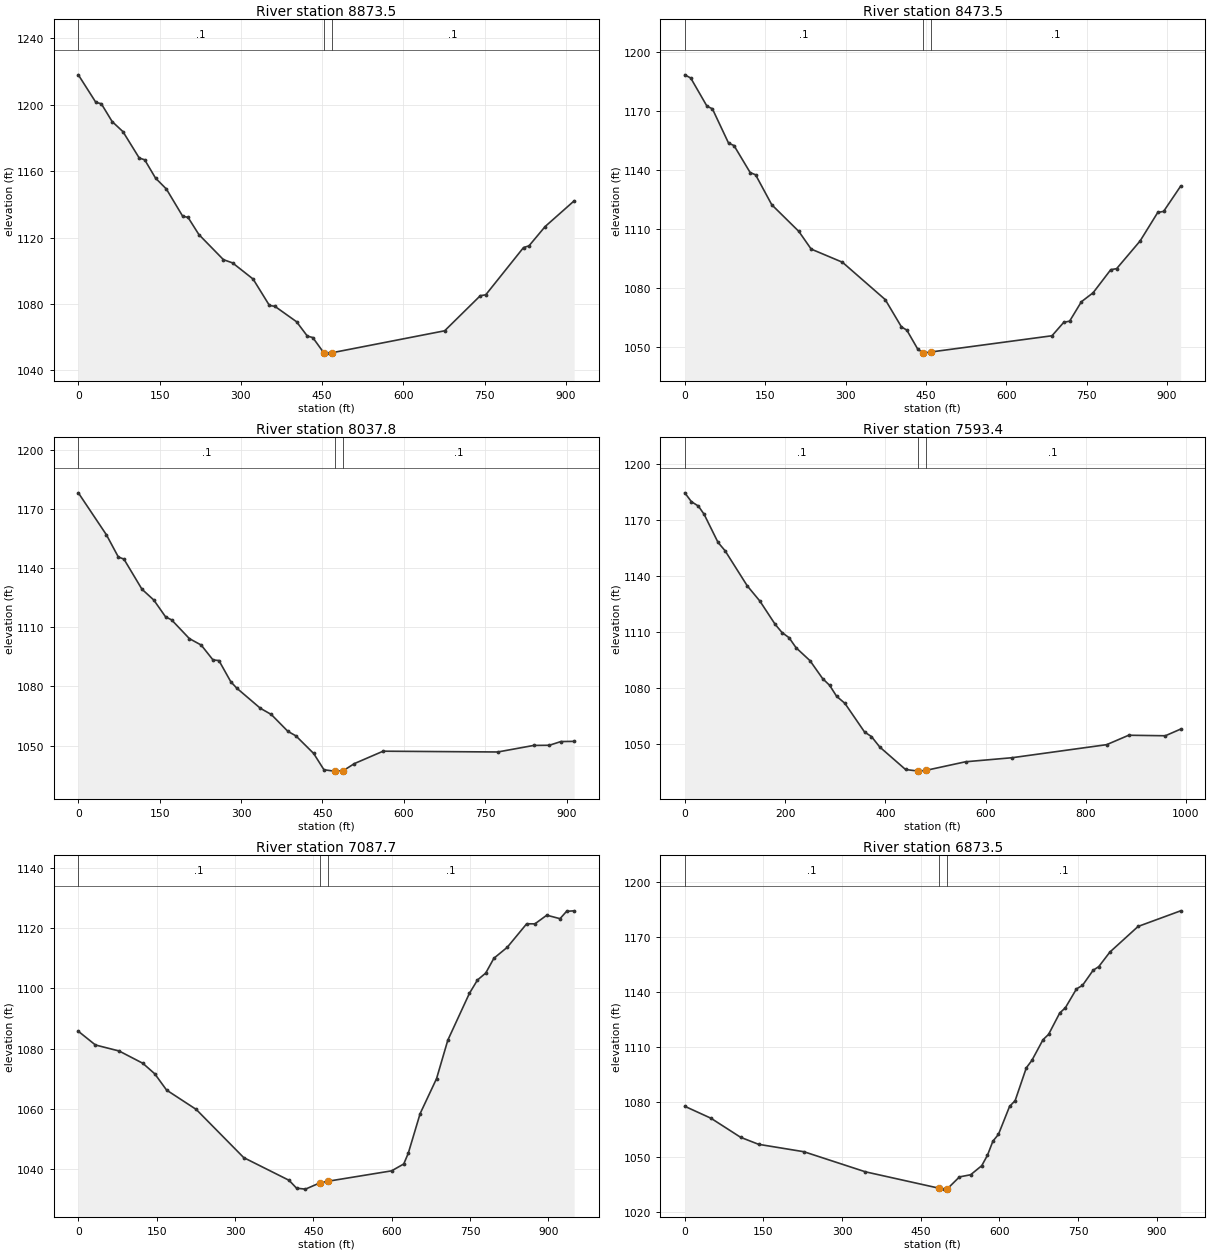
Type RM Length L Ch R = 1 ,8873.5  ,398.664,400,407.179
XS GIS Cut Line= 3
     1732741.862      399008.967      1732657.68      399461.887
      1732584.12      399910.283
#Sta/Elev= 30
       0 1218.06    32.4 1201.44    42.4 1200.65    62.4 1189.91    82.4 1183.81
   112.4 1167.94   122.5 1166.86   142.5 1155.82   162.5 1149.26   192.5 1132.92
   202.5 1132.15   222.5 1121.82   267.8 1106.69   284.7 1104.74   322.6    1095
   352.7 1079.09   362.7 1078.59   402.7 1069.31   422.7 1060.63   432.7 1059.77
   453.2  1050.5   461.9 1050.38   468.2 1050.61   676.1 1063.84   741.9 1084.99
   751.9 1085.51   821.7 1114.01   831.7    1115   861.6 1126.67   915.1 1142.13
#Mann= 3 , 0 , 0
       0      .1       0   453.2    .045       0   468.2      .1       0
Bank Sta=453.2,468.2
XS Rating Curve= 0 ,0
Exp/Cntr=0.3,0.1

Type RM Length L Ch R = 1 ,8473.5  ,427.703,435.712,423.2
XS GIS Cut Line= 3
     1732407.207      398882.336     1732309.212      399323.317
     1732100.331      399748.236
#Sta/Elev= 30
       0 1188.37    11.1 1186.73    41.4  1172.4    51.5 1171.09    81.7  1153.6
    91.8 1152.39     122 1138.63   132.1 1137.51   162.3 1122.26   212.7 1108.73
   235.8 1099.71   294.1 1093.02     374 1074.01   404.3  1060.1   414.3 1058.48
   434.5  1048.9   444.2 1046.84   444.6 1046.77   459.2 1047.35   685.2 1055.61
   707.1 1062.43   718.1 1063.05     740 1072.91   761.9 1077.48   794.8 1089.22
   805.8 1089.75   849.6 1103.84   882.5 1118.34   893.5  1118.9   925.2 1131.72
#Mann= 3 , 0 , 0
       0      .1       0   444.2    .045       0   459.2      .1       0
Bank Sta=444.2,459.2
XS Rating Curve= 0 ,0
Exp/Cntr=0.3,0.1

Type RM Length L Ch R = 1 ,8037.8  ,425.824,444.462,452.184
XS GIS Cut Line= 3
     1732153.007      398777.602     1731948.925      399202.537
     1731787.287      399614.716
#Sta/Elev= 30
       0 1178.28    51.8 1156.96    73.7 1145.73    84.1 1144.62   117.3 1129.35
   139.2 1123.84     161 1115.26   171.9 1113.81   204.7 1104.28   226.5 1101.01
   248.3 1093.45   259.2 1093.15   281.1 1082.38     292 1079.16   335.6 1068.91
   355.7 1065.77   386.4 1057.19   401.1 1054.92   433.9 1045.96   452.8 1037.71
   471.4 1037.01   472.9 1037.02   487.9 1037.16   509.1 1040.86   561.9 1047.13
   773.3 1046.73   839.4 1050.05   868.4 1050.14   889.6 1052.02   914.1 1052.12
#Mann= 3 , 0 , 0
       0      .1       0   472.9    .045       0   487.9      .1       0
Bank Sta=472.9,487.9
XS Rating Curve= 0 ,0
Exp/Cntr=0.3,0.1

Type RM Length L Ch R = 1 ,7593.4  ,502.926,505.635,503.115
XS GIS Cut Line= 3
     1732045.909      398677.211        1731759.       398964.12
     1731326.981      399356.427
#Sta/Elev= 30
       0 1184.52    13.2 1179.78    27.1 1177.42    38.5 1173.04    66.3 1157.96
    80.3 1153.52   124.6 1134.69   149.8 1126.53   180.2  1114.1   194.1 1109.63
     208 1106.92     222 1101.52   249.8  1094.6   275.1 1084.96     289 1081.38
   302.9 1075.51   319.4 1071.75   358.6 1056.39   372.5 1053.91     389 1048.33
   440.4 1036.29   465.7 1035.42     467 1035.41   480.7 1035.79   560.1 1040.42
   653.1  1042.6   841.8 1049.59   885.7 1054.64   958.8 1054.36   989.3 1057.92
#Mann= 3 , 0 , 0
       0      .1       0   465.7    .045       0   480.7      .1       0
Bank Sta=465.7,480.7
XS Rating Curve= 0 ,0
Exp/Cntr=0.3,0.1

Type RM Length L Ch R = 1 ,7087.7  ,205.583,214.191,225.974
XS GIS Cut Line= 3
     1731761.604      398488.382     1731399.353      398697.415
     1731066.228      399111.133
#Sta/Elev= 30
       0 1085.79    32.7 1081.25    78.1 1079.25   123.5 1075.18   146.3  1071.7
     169  1066.3   225.8 1059.88   316.7 1043.92   403.5  1036.4   417.9 1033.79
   434.9 1033.48   462.9 1035.58   477.9 1036.09   599.9 1039.54   623.1 1041.82
   631.7 1045.34   654.5 1058.52   685.9 1070.09   707.5 1082.85   748.7 1098.31
   764.3 1102.79     780 1105.06   795.7 1109.98   821.2  1113.6   858.5 1121.41
   874.2 1121.38     897 1124.25   922.3  1123.1   934.9 1125.54   949.4  1125.7
#Mann= 3 , 0 , 0
       0      .1       0   462.9    .045       0   477.9      .1       0
Bank Sta=462.9,477.9
XS Rating Curve= 0 ,0
Exp/Cntr=0.3,0.1

Type RM Length L Ch R = 1 ,6873.5  ,393.525,400,414.658
XS GIS Cut Line= 3
     1731638.875      398360.767     1731210.846      398605.288
      1730791.73        398776.2
#Sta/Elev= 30
       0 1077.69    49.9 1071.16   106.5 1060.74   140.7 1056.91   227.3 1052.85
   344.5 1041.88   485.4 1032.89   494.2 1032.42   500.4 1032.51   523.8  1039.1
   545.1 1040.27   566.3 1045.23   577.2 1050.92   587.6 1058.64   598.2 1062.36
   619.4 1077.64     630 1080.78   651.3 1098.71   661.9 1102.76   683.2  1114.1
   693.8    1117   715.1 1128.71   725.7 1131.49     747 1141.85   758.4 1143.75
   778.8 1152.04   789.5 1154.02   810.7 1161.97   864.5 1175.98   945.6 1184.51
#Mann= 3 , 0 , 0
       0      .1       0   485.4    .045       0   500.4      .1       0
Bank Sta=485.4,500.4
XS Rating Curve= 0 ,0
Exp/Cntr=0.3,0.1

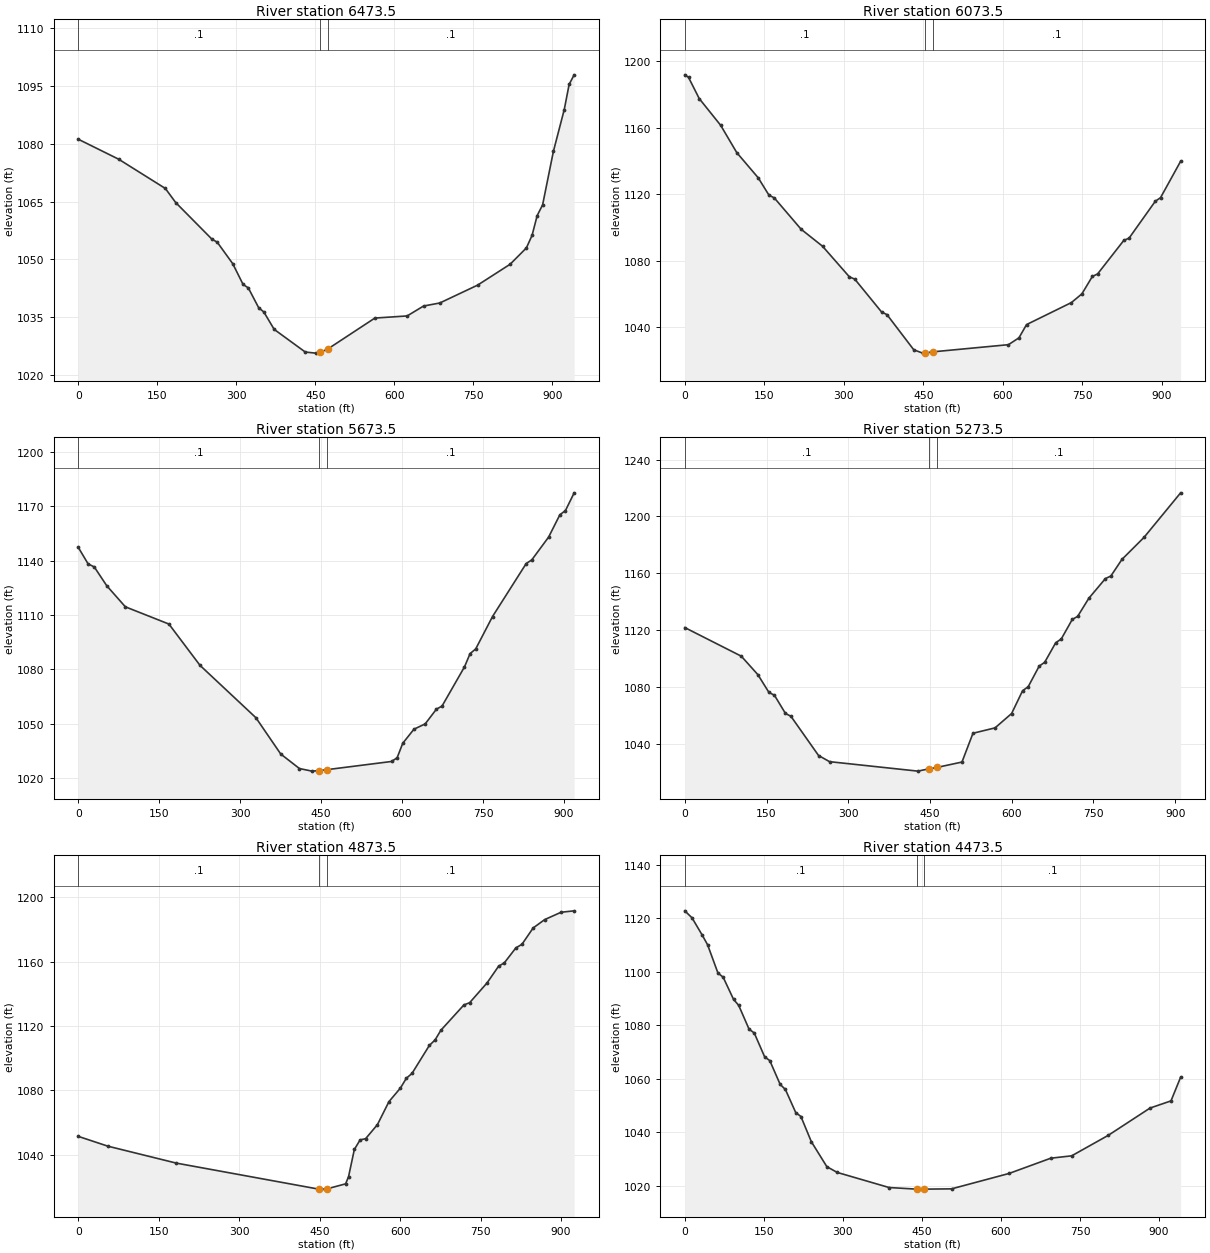
Type RM Length L Ch R = 1 ,6473.5  ,397.101,400,394.758
XS GIS Cut Line= 3
     1731613.126      398259.995     1731147.319      398259.386
     1730691.925       398122.94
#Sta/Elev= 30
       0 1081.17    76.6 1075.99   165.2  1068.4   184.8 1064.75   253.7 1055.23
   263.6 1054.47   293.1 1048.88   312.8 1043.48   322.6 1042.61   342.3 1037.46
   352.1 1036.35   371.8 1031.83   430.8 1025.95   450.5 1025.67   458.3 1025.85
   473.3 1026.72   562.9 1034.77   624.2 1035.32   655.3 1037.89   686.1 1038.68
     758 1043.32   819.7 1048.74   850.5 1052.97   861.3 1056.23     871 1061.36
   881.3 1064.14   901.8 1078.03   922.4 1088.87   931.7 1095.42   941.2 1097.89
#Mann= 3 , 0 , 0
       0      .1       0   458.3    .045       0   473.3      .1       0
Bank Sta=458.3,473.3
XS Rating Curve= 0 ,0
Exp/Cntr=0.3,0.1

Type RM Length L Ch R = 1 ,6073.5  ,407.452,400,393.223
XS GIS Cut Line= 3
     1731631.869      397787.498     1731184.245      397895.428
     1730711.603      397944.945
#Sta/Elev= 30
       0 1191.75       7 1190.24    27.2 1177.49    67.7 1161.39    98.1 1144.96
   138.6 1129.81   158.8  1119.4   168.9 1117.74   219.5  1098.9     260 1088.66
   310.6 1070.27   320.8 1068.89   371.4 1049.12   381.5 1047.57   432.1  1026.4
     449  1024.4     453 1024.51     468 1025.17   610.8 1029.48   630.6 1033.59
   644.9 1041.55   729.6  1054.8   749.4 1060.04   769.1  1070.5     779 1072.02
   828.5 1092.19   838.4 1093.54   887.9 1115.72   897.8 1117.88   935.7 1139.76
#Mann= 3 , 0 , 0
       0      .1       0     453    .045       0     468      .1       0
Bank Sta=453,468
XS Rating Curve= 0 ,0
Exp/Cntr=0.3,0.1

Type RM Length L Ch R = 1 ,5673.5  ,392.997,400,401.995
XS GIS Cut Line= 3
     1731522.453      397285.401     1731135.133      397521.275
     1730694.747      397672.091
#Sta/Elev= 30
       0 1147.32    18.1 1138.26    29.6 1136.55    52.7 1126.17    87.2 1114.54
   167.9 1105.03   225.5 1082.23   329.1 1053.32   375.2 1033.25   409.8 1025.25
   432.9 1023.82     446  1024.1     461 1024.64   580.5 1029.15   590.9  1031.2
   601.3 1039.21   622.1 1046.98   642.9  1049.9   663.7 1058.04   674.1 1059.74
   715.7 1081.36   726.1 1088.72   736.5 1091.28   767.7 1109.19   830.1 1138.44
   840.5 1140.47   871.7 1153.07   892.5 1165.36   902.9 1167.72     919 1177.49
#Mann= 3 , 0 , 0
       0      .1       0     446    .045       0     461      .1       0
Bank Sta=446,461
XS Rating Curve= 0 ,0
Exp/Cntr=0.3,0.1

Type RM Length L Ch R = 1 ,5273.5  ,396.779,400,395.126
XS GIS Cut Line= 3
      1731440.55      397040.682     1730998.291      397147.602
     1730556.032      397254.522
#Sta/Elev= 30
       0 1121.75   103.7  1101.6   134.1 1088.62   154.4 1076.11   164.5 1074.12
   184.7 1061.32   194.8 1059.29   245.5 1031.69   265.7 1027.36   427.7  1020.7
   447.5 1022.26   462.5 1023.28   508.7 1027.09   528.9 1047.36   569.4 1051.14
   599.8 1061.24     620 1077.33   630.2 1080.07   650.4 1094.62   660.5  1097.3
   680.8  1111.1   690.9  1113.7   711.1 1127.44     721 1129.62   741.5 1142.35
   771.9 1156.21     782 1158.05   802.3 1169.73   842.7 1185.18     910 1216.59
#Mann= 3 , 0 , 0
       0      .1       0   447.5    .045       0   462.5      .1       0
Bank Sta=447.5,462.5
XS Rating Curve= 0 ,0
Exp/Cntr=0.3,0.1

Type RM Length L Ch R = 1 ,4873.5  ,396.461,400,413.803
XS GIS Cut Line= 3
     1731345.296      396721.452     1730891.971      396765.292
     1730462.144      396955.089
#Sta/Elev= 30
       0 1051.44      55 1045.37   182.7 1034.85   447.9 1018.72   453.2  1018.7
   462.9 1018.81   498.3 1021.98   503.8 1026.45   514.6 1043.33   525.3 1049.26
   535.6 1050.02   557.6 1058.72   579.1 1073.02   600.6 1081.48   611.4 1087.48
   622.1 1090.54   654.4 1107.89   665.2 1111.36   675.9 1117.32   718.9 1133.06
   729.5 1134.42     762 1146.71   783.5 1157.07   794.2 1159.18   815.8 1168.48
     827 1170.66     848 1180.85   869.5 1186.03     900 1190.58   924.4 1191.47
#Mann= 3 , 0 , 0
       0      .1       0   447.9    .045       0   462.9      .1       0
Bank Sta=447.9,462.9
XS Rating Curve= 0 ,0
Exp/Cntr=0.3,0.1

Type RM Length L Ch R = 1 ,4473.5  ,409.753,400,389.855
XS GIS Cut Line= 3
     1731284.576       396438.02      1730837.19      396441.387
     1730347.414      396380.273
#Sta/Elev= 30
       0 1122.73    13.7 1120.11    33.4 1113.54    43.3 1110.02    62.9 1099.48
    72.8 1097.92    92.5 1089.64   102.3 1087.39     122 1078.48   131.8 1077.08
   151.5 1068.17   161.3 1066.74     181 1057.84   190.9 1055.96   210.5 1047.33
   220.4 1045.84   240.1 1036.45   269.6 1027.09   289.3 1024.94   387.7  1019.3
   439.9  1018.7   454.9  1018.7   506.2  1018.8   615.3 1024.55   694.6 1030.26
   734.3 1031.15   803.7 1038.81     883 1049.01   922.7 1051.68     941 1060.53
#Mann= 3 , 0 , 0
       0      .1       0   439.9    .045       0   454.9      .1       0
Bank Sta=439.9,454.9
XS Rating Curve= 0 ,0
Exp/Cntr=0.3,0.1

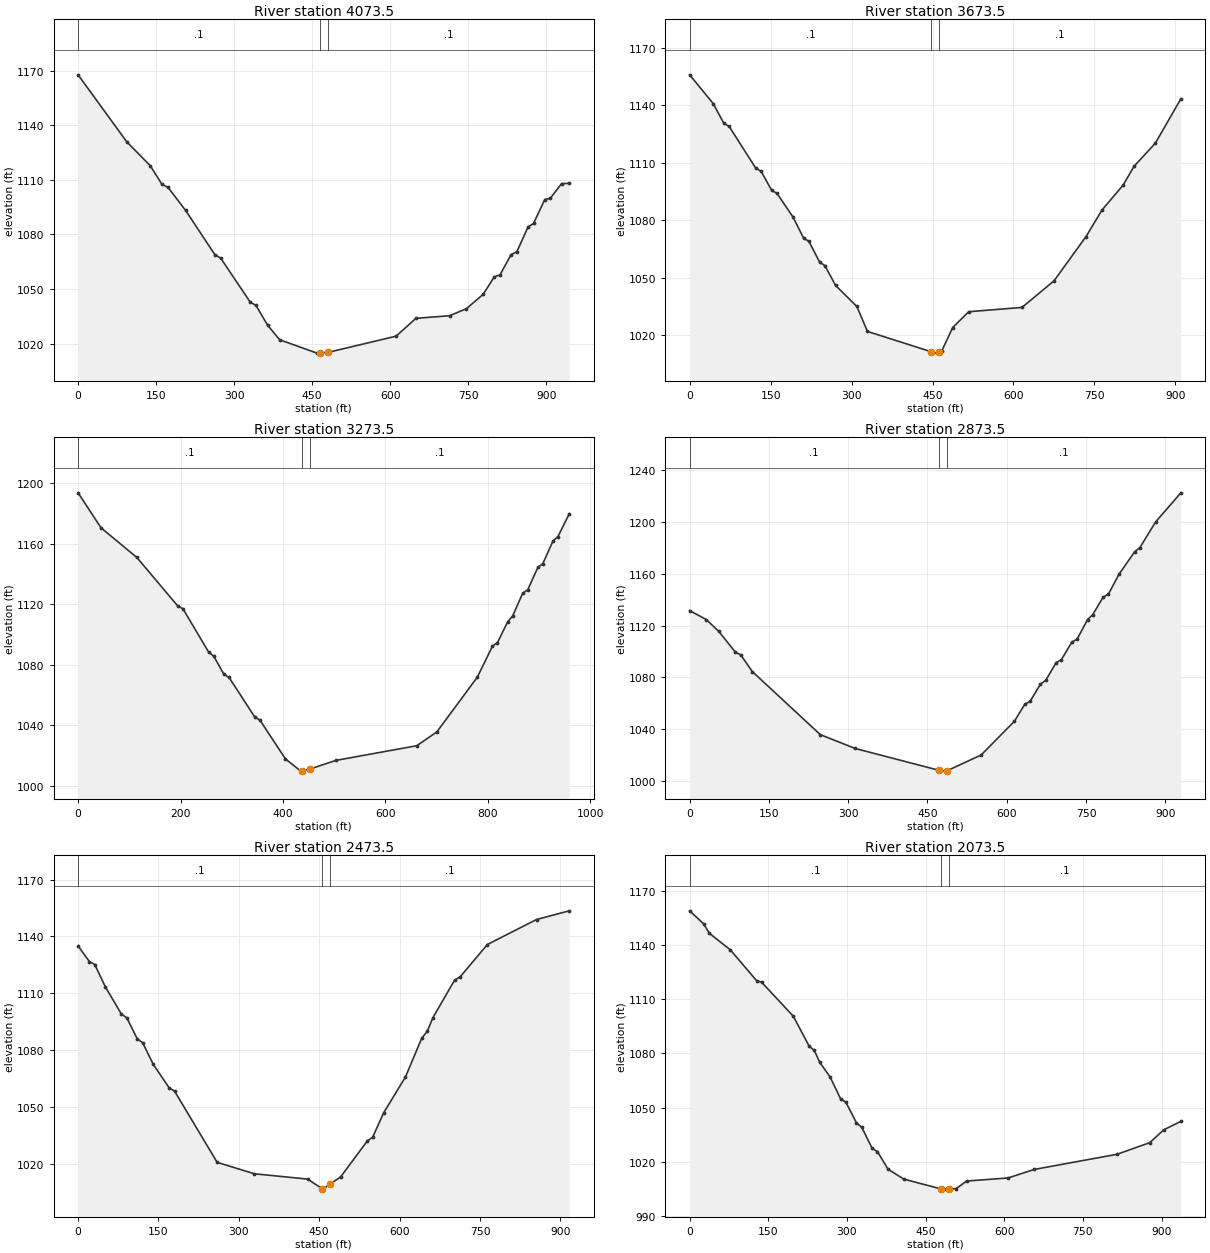
Type RM Length L Ch R = 1 ,4073.5  ,387.873,400,408.177
XS GIS Cut Line= 3
     1731175.276      395849.994     1730763.902      396081.542
     1730332.273       396273.19
#Sta/Elev= 30
       0 1167.69    93.6 1130.86   138.8 1117.74   161.3 1107.48   172.6 1105.95
   206.5 1093.28     263 1068.86   274.3 1066.92   330.7 1042.88     342 1040.95
   364.6 1030.03   387.4 1022.13   459.2 1014.78   464.6 1014.83   479.6 1015.13
   611.2 1024.08   649.5  1033.9   714.1 1035.34   746.4 1039.17   778.7 1047.08
   800.2 1056.73     811 1057.71   832.5 1068.97   843.3 1070.37   864.8 1083.97
   875.6 1086.04   897.1 1099.16   907.9 1099.89   929.4 1107.91   944.3 1108.07
#Mann= 3 , 0 , 0
       0      .1       0   464.6    .045       0   479.6      .1       0
Bank Sta=464.6,479.6
XS Rating Curve= 0 ,0
Exp/Cntr=0.3,0.1

Type RM Length L Ch R = 1 ,3673.5  ,397.448,400,397.221
XS GIS Cut Line= 3
     1731156.891      395735.674     1730702.599       395706.66
     1730249.555      395664.932
#Sta/Elev= 30
       0 1155.97    43.6 1140.99    63.3 1130.68    73.2 1129.06   122.5 1107.26
   132.3  1105.7     152 1095.67   161.9  1094.1   191.5 1081.77   211.2 1070.75
   221.1 1069.02   240.8 1058.29   250.6  1056.4   270.4  1046.1   309.8 1035.09
   329.5 1022.08   447.7 1011.47   457.7 1010.76   462.7 1011.35   467.1 1011.87
   487.4 1024.11     517 1032.36   615.8 1034.61   675.1 1048.45   734.4 1071.54
     764 1085.39   803.6 1098.56   823.3 1108.19   862.9  1120.3   910.2 1143.44
#Mann= 3 , 0 , 0
       0      .1       0   447.7    .045       0   462.7      .1       0
Bank Sta=447.7,462.7
XS Rating Curve= 0 ,0
Exp/Cntr=0.3,0.1

Type RM Length L Ch R = 1 ,3273.5  ,414.261,400,397.764
XS GIS Cut Line= 3
     1731255.808      395413.537     1730818.473      395334.023
     1730304.174      395347.407
#Sta/Elev= 30
       0 1193.56    44.7 1170.48   114.7  1150.9   194.8 1118.79   204.8 1116.98
   254.8 1088.44   264.8 1085.78   284.8 1073.68   294.8 1071.73   344.8 1045.61
   354.8 1043.62   404.8 1017.97   434.8 1009.87     437 1010.07     452 1011.18
   503.8 1016.99   661.3 1026.64   700.4 1035.75   779.5 1071.91     809 1092.35
   818.8  1094.7   838.5 1108.33   848.4 1112.31     868 1127.27   877.9 1129.61
   897.6 1144.29   907.4 1146.86   927.1 1161.76   936.9 1164.71     959 1179.81
#Mann= 3 , 0 , 0
       0      .1       0     437    .045       0     452      .1       0
Bank Sta=437,452
XS Rating Curve= 0 ,0
Exp/Cntr=0.3,0.1

Type RM Length L Ch R = 1 ,2873.5  ,393.168,400,396.429
XS GIS Cut Line= 3
     1731103.139       394806.39     1730667.839       395005.08
     1730219.598      395053.538
#Sta/Elev= 30
       0 1131.52    31.4 1124.59    55.1  1115.5    86.1 1099.67    96.9 1097.28
   118.5 1084.56   247.2 1036.01   313.2 1025.36     471 1008.64   485.6 1007.92
     486 1008.02   551.6 1020.37   614.3 1046.21   634.1 1059.36     644 1061.56
   663.8  1074.9   673.7 1077.78   693.5 1091.46   703.4 1093.75   723.2 1107.23
   733.1 1109.53   752.9 1124.57   762.7 1128.39   782.5 1141.88   792.4 1144.18
   812.2 1159.34   841.9 1176.73   851.8 1179.94   881.5 1199.65   929.4 1222.14
#Mann= 3 , 0 , 0
       0      .1       0     471    .045       0     486      .1       0
Bank Sta=471,486
XS Rating Curve= 0 ,0
Exp/Cntr=0.3,0.1

Type RM Length L Ch R = 1 ,2473.5  ,392.714,400,403.143
XS GIS Cut Line= 3
     1731016.264      394561.921     1730557.435      394624.063
     1730119.595      394742.537
#Sta/Elev= 30
       0    1135    21.1 1126.76    31.1  1125.2    50.9 1113.44    80.7 1099.13
      91 1097.09   110.5 1085.97   120.4 1084.06   140.3 1072.59   170.1 1060.18
     180 1058.49   259.5 1020.97     329 1014.94   428.3 1012.15   455.5 1007.07
   457.4 1006.86   470.5 1009.63   489.9  1013.3   539.5 1032.16   549.7 1034.22
     570 1046.97   610.8 1065.92   641.4 1086.46   651.6 1090.04   661.8 1097.04
   702.6 1117.01   712.8 1118.67   763.7 1135.75   855.5 1148.93   916.6  1153.5
#Mann= 3 , 0 , 0
       0      .1       0   455.5    .045       0   470.5      .1       0
Bank Sta=455.5,470.5
XS Rating Curve= 0 ,0
Exp/Cntr=0.3,0.1

Type RM Length L Ch R = 1 ,2073.5  ,409.324,400,396.525
XS GIS Cut Line= 3
     1731031.972      394332.611     1730553.757      394238.787
     1730106.961       394287.53
#Sta/Elev= 30
       0 1158.99    26.9 1151.73    37.4 1146.59    77.5  1137.4   127.6 1120.35
   137.6 1119.36   197.8 1100.59   227.9 1084.05   237.9 1081.67   247.9 1075.15
     268 1066.95     288 1054.79   298.1 1052.97   318.1 1041.57   328.2 1039.13
   348.2  1027.4   358.2 1025.64   378.3 1015.96   408.4 1010.44   479.8 1004.98
   488.6  1004.9   494.8 1004.95   508.4 1005.18   528.2 1009.38   607.3 1011.08
   656.8 1015.78   815.2  1024.2   877.5 1030.63   904.3 1037.78   936.8 1042.42
#Mann= 3 , 0 , 0
       0      .1       0   479.8    .045       0   494.8      .1       0
Bank Sta=479.8,494.8
XS Rating Curve= 0 ,0
Exp/Cntr=0.3,0.1

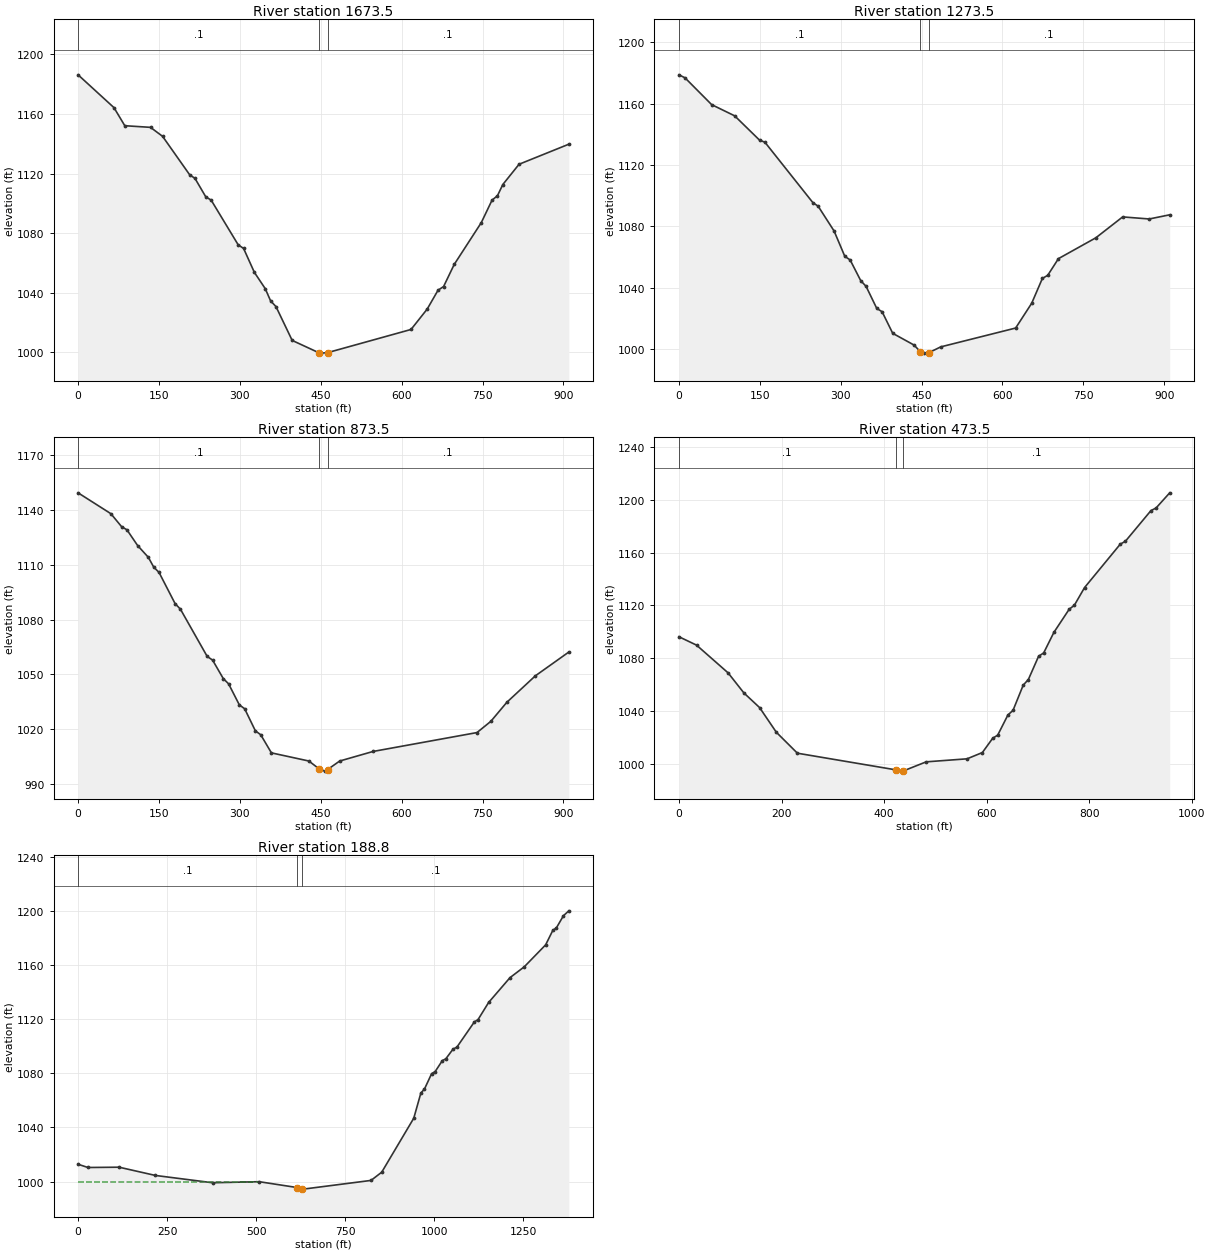
Type RM Length L Ch R = 1 ,1673.5  ,393.749,400,407.129
XS GIS Cut Line= 3
      1731011.52       393798.32     1730564.451      393882.901
     1730117.381      393967.481
#Sta/Elev= 30
       0 1186.23    66.6  1164.2    86.6  1152.1   134.3    1151   156.7 1144.97
   206.8 1119.24   216.8 1116.75   236.8 1104.38   246.8 1102.18   296.9  1072.2
   306.9 1069.78   326.9 1053.73     347 1042.84     357 1034.62     367 1030.75
     397 1008.09   447.5  999.65   449.9  999.56   462.5  999.87   617.4 1015.43
   647.4 1029.13   667.4 1041.72   677.8 1044.25   697.5 1059.08   747.6 1087.05
   767.6 1102.17   777.6  1105.1   787.6 1112.65   817.7 1126.24     910  1139.7
#Mann= 3 , 0 , 0
       0      .1       0   447.5    .045       0   462.5      .1       0
Bank Sta=447.5,462.5
XS Rating Curve= 0 ,0
Exp/Cntr=0.3,0.1

Type RM Length L Ch R = 1 ,1273.5  ,399.122,400,400
XS GIS Cut Line= 3
     1730986.797      393526.726     1730533.228      393485.706
     1730082.094      393427.095
#Sta/Elev= 30
       0  1178.7    11.2 1176.75    60.6 1159.31   103.3 1152.01   149.5 1136.18
   159.4 1134.84   248.3 1095.54   258.2 1093.16   287.8    1077   307.6 1060.56
   317.5  1058.2   337.2  1044.7   347.1    1041   366.9 1026.64   376.8 1024.49
   396.5 1010.43   436.1 1002.79   447.9   998.4   455.4  997.54   462.9  997.74
   485.6 1001.61   624.5 1013.87   654.3 1030.01   674.1 1046.17     684 1048.19
   703.9 1059.05   773.3 1072.62     823 1086.21   872.3 1084.87   910.3 1087.58
#Mann= 3 , 0 , 0
       0      .1       0   447.9    .045       0   462.9      .1       0
Bank Sta=447.9,462.9
XS Rating Curve= 0 ,0
Exp/Cntr=0.3,0.1

Type RM Length L Ch R = 1 ,873.5   ,387.197,400,399.244
XS GIS Cut Line= 3
     1731035.971      393147.661     1730584.763       393089.04
     1730133.555      393030.419
#Sta/Elev= 30
       0 1149.43    60.8 1138.01    80.7 1130.89    90.6 1129.18   110.5 1120.53
   130.3 1114.11   140.2 1108.78   150.1 1105.86   179.9 1088.76   189.8 1085.71
   239.4 1059.84   249.4 1057.84   269.2 1047.73   279.1 1044.83     299 1033.32
   308.9 1031.18   328.8 1019.08   338.7 1016.94   358.5 1007.03     428 1002.56
   447.5  998.14   457.7  997.03   462.5  997.87   485.1 1002.56   547.1 1007.81
   739.7 1018.15   765.4  1024.3   795.1 1034.74     848 1049.23     910 1062.25
#Mann= 3 , 0 , 0
       0      .1       0   447.5    .045       0   462.5      .1       0
Bank Sta=447.5,462.5
XS Rating Curve= 0 ,0
Exp/Cntr=0.3,0.1

Type RM Length L Ch R = 1 ,473.5   ,299.339,284.779,283.778
XS GIS Cut Line= 3
     1731062.578      393001.275     1730732.108      392726.254
     1730211.308      392644.041
#Sta/Elev= 30
       0 1096.23    34.3 1089.87    95.8 1068.85   126.6 1053.64   157.3  1042.5
   189.9 1023.81     231 1007.91   422.4  995.33   434.5  994.32   437.4  994.43
   482.2 1001.36   561.9 1003.65   591.8 1008.42   611.8 1019.18   621.7 1021.63
   641.6  1036.9   651.6 1040.44   671.5 1059.56   681.5  1063.8   701.4 1081.39
   711.4    1084   731.3 1099.56   761.2 1117.15   771.1 1120.05   791.1 1133.53
   860.8 1166.47   870.8 1168.67   920.6 1191.91   930.5 1193.86   957.2 1205.38
#Mann= 3 , 0 , 0
       0      .1       0   422.4    .045       0   437.4      .1       0
Bank Sta=422.4,437.4
XS Rating Curve= 0 ,0
Exp/Cntr=0.3,0.1

Type RM Length L Ch R = 1 ,188.8   ,226.046,188.769,151.024
XS GIS Cut Line= 3
     1731415.517      392939.032     1730987.174      392547.058
     1730203.226      392401.583
#Sta/Elev= 30
       0 1012.76    27.7 1010.36   115.2 1010.58   217.2 1004.48   377.5  999.08
   508.7  999.85   615.1  995.53   630.1  994.49   632.4  994.36   822.5  1000.8
   852.6 1006.88   942.6 1046.83   962.5 1065.42   972.7 1068.44   992.7 1079.76
  1002.7 1081.35  1022.7 1089.38  1032.7 1090.81  1052.7 1097.87  1063.8 1099.44
  1112.8  1118.1  1122.8 1119.67  1152.8 1132.45  1212.8 1150.81  1252.9 1158.84
  1312.9 1175.08  1332.9 1185.71    1343 1187.61    1363 1196.67    1378 1200.24
#Mann= 3 , 0 , 0
       0      .1       0   615.1    .045       0   630.1      .1       0
#XS Ineff= 2 , 0
          504.18    1000
Permanent Ineff=
       F       F
Bank Sta=615.1,630.1
XS Rating Curve= 0 ,0
Exp/Cntr=0.3,0.1

Chan Stop Cuts=-1
Use User Specified Reach Order=0